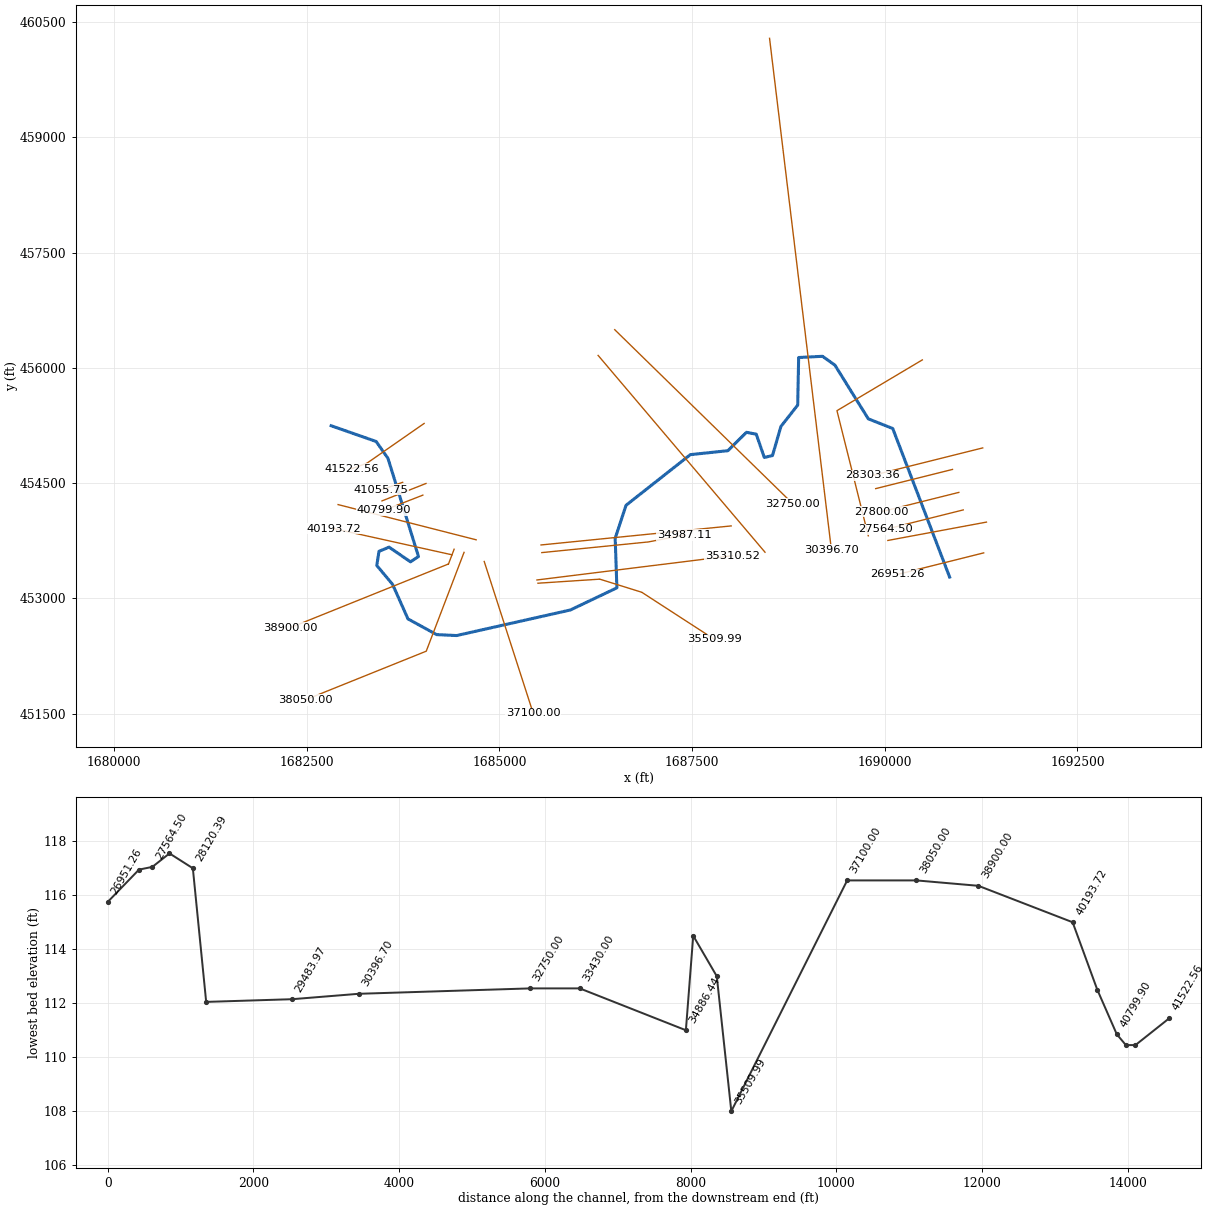
--- HampdenBridges.prj (project) ---

Proj Title=Hampden Bridges
Current Plan=p02
Current HD=h01
Default Exp/Contr=0.3,0.1
English Units
Geom File=g01
Geom File=g02
Flow File=f01
Flow File=f02
Plan File=p01
Plan File=p02
Plan File=p03
Plan File=p04
HD File=h01
Y Axis Title=Elevation
X Axis Title(PF)=Main Channel Distance
X Axis Title(XS)=Station
BEGIN DESCRIPTION:
END DESCRIPTION:
DSS Export Rating Curves= 0
DSS Export Rating Curve Sorted= 0
DSS Export Volume Flow Curves= 0
DXF OffsetX= 0
DXF OffsetY= 0
DXF ScaleX= 1
DXF ScaleY= 10

--- HampdenBridges.p02 (plan) ---

Plan Title=Existing Condition MEDOT Flows
Program Version=5.03
Short Identifier=exist MEDOT
Geom File=g01
Flow File=f02
Mixed Flow
K Sum by GR= 0
Std Step Tol= 0.01
Critical Tol= 0.01
Num of Std Step Trials= 20
Max Error Tol= 0.3
Flow Tol Ratio= 0.001
Split Flow NTrial= 30
Split Flow Tol= 0.02
Split Flow Ratio= 0.02
Log Output Level= 0
Friction Slope Method= 1
Unsteady Friction Slope Method= 2
Unsteady Bridges Friction Slope Method= 1
Parabolic Critical Depth
Global Vel Dist= 0 , 0 , 0
Global Log Level= 0
CheckData=True
Encroach Param=-1 ,0,0, 0
Computation Interval=1MIN
Output Interval=1HOUR
Instantaneous Interval=1HOUR
Mapping Interval=1HOUR
Run HTab= 0
Run UNet= 0
Run Sediment= 0
Run PostProcess= 0
Run WQNet= 0
Run RASMapper= 0
UNET Theta= 1
UNET Theta Warmup= 1
UNET ZTol= 0.02
UNET ZSATol= 0.02
UNET MxIter= 20
UNET Max Iter WO Improvement= 0
UNET MaxInSteps= 0
UNET DtIC= 0
UNET DtMin= 0
UNET MaxCRTS= 20
UNET WFStab= 2
UNET SFStab= 1
UNET WFX= 1
UNET SFX= 1
UNET DSS MLevel= 4
UNET Pardiso=0
UNET DZMax Abort= 100
UNET Use Existing IB Tables=-1
UNET Froude Reduction=False
UNET Froude Limit= 0.8
UNET Froude Power= 4
UNET Time Slicing=0,0, 5
UNET D1 Cores= 0
UNET D2 Coriolis=0
UNET D2 Cores= 0
UNET D2 Theta= 1
UNET D2 Theta Warmup= 1
UNET D2 Z Tol= 0.01
UNET D2 Volume Tol= 0.01
UNET D2 Max Iterations= 20
UNET D2 Equation= 0
UNET D2 RampUpFraction=0.1
UNET D2 TimeSlices= 1
UNET D2 BCVolumeCheck=0
UNET D1D2 MaxIter= 0
UNET D1D2 ZTol=0.01
UNET D1D2 QTol=0.1
UNET D1D2 MinQTol=1
Write IC File= 0
Write IC File at Fixed DateTime=0
Write IC File at Sim End=0
Echo Input=False
Echo Parameters=False
Echo Output=False
Write Detailed= 0
HDF Write Warmup=0
HDF Write Time Slices=0
HDF Flush=0
HDF Face Node Velocities=0
HDF Compression= 1
HDF Chunk Size= 1
HDF Spatial Parts= 1
HDF Use Max Rows=0
HDF Fixed Rows= 1
Calibration Method= 0
Calibration Iterations= 20
Calibration Max Change=0.05
Calibration Tolerance=0.2
Calibration Maximum=1.5
Calibration Minimum=0.5
Calibration Optimization Method= 1
WQ AD Non Conservative
WQ ULTIMATE=-1
WQ Max Comp Step=1HOUR
WQ Output Interval=15MIN
WQ Output Selected Increments= 0
WQ Output face flow=0
WQ Output face velocity=0
WQ Output face area=0
WQ Output face dispersion=0
WQ Output cell volume=0
WQ Output cell surface area=0
WQ Output cell continuity=0
WQ Output cumulative cell continuity=0
WQ Output face conc=0
WQ Output face dconc_dx=0
WQ Output face courant=0
WQ Output face peclet=0
WQ Output face adv mass=0
WQ Output face disp mass=0
WQ Output cell mass=0
WQ Output cell source sink temp=0
WQ Output nsm pathways=0
WQ Output nsm derived pathways=0
WQ Output MaxMinRange=-1
WQ Daily Max Min Mean=-1
WQ Daily Range=0
WQ Daily Time=0
WQ Create Restart=0
WQ Fixed Restart=0
WQ System Summary=0
WQ Write To DSS=0
WQ Use Fixed Temperature=0
Sorting and Armoring Iterations= 10
XS Update Threshold= 0.02
Bed Roughness Predictor= 0
Hydraulics Update Threshold= 0.02
Energy Slope Method= 1
Volume Change Method= 1
Sediment Retention Method= 0
XS Weighting Method= 0
Number of US Weighted Cross Sections= 1
Number of DS Weighted Cross Sections= 1
Upstream XS Weight=0
Main XS Weight=1
Downstream XS Weight=0
Number of DS XS's Weighted with US Boundary= 1
Upstream Boundary Weight= 1
Weight of XSs Associated with US Boundary= 0
Number of US XS's Weighted with DS Boundary= 1
Downstream Boundary Weight= 0.5
Weight of XSs Associated with DS Boundary= 0.5
Percentile Method= 0
Sediment Output Level= 4
Mass or Volume Output= 0
Output Increment Type= 1
Profile and TS Output Increment= 1
XS Output Flag= 0
XS Output Increment= 10
Write Gradation File= 0
Read Gradation Hotstart= 0
Write HDF5 File= 1
Write DSS Sediment File= 0
SV Curve= 0
Specific Gage Flag= 0

--- HampdenBridges.p01 (plan) ---

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Plan Title=Existing Condition
Short Identifier=Exist
Geom File=g01
Flow File=f01
Subcritical Flow

--- HampdenBridges.p03 (plan) ---

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Plan Title=junkProposed 2 span
Short Identifier=prop2spanjunk
Geom File=g02
Flow File=f02
Subcritical Flow

--- HampdenBridges.p04 (plan) ---

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Plan Title=Proposed Bridge Plan
Short Identifier=PROPBRIDGE
Geom File=g02
Flow File=f02

--- HampdenBridges.f02 (steady flow) ---

Flow Title=MEDOT FLOWS
Program Version=5.03
Number of Profiles= 6
Profile Names=1.1 year,10 year,25 year,50 year,100 year,500 year
River Rch & RM=Souadabscook Str,Reach           ,41522.56
    1210    3640    4440    5040    5680    7180
Boundary for River Rch & Prof#=Souadabscook Str,Reach           , 1
Up Type= 3
Up Slope=0.001667
Dn Type= 3
Dn Slope=0.00262
Boundary for River Rch & Prof#=Souadabscook Str,Reach           , 2
Up Type= 3
Up Slope=0.001667
Dn Type= 3
Dn Slope=0.00262
Boundary for River Rch & Prof#=Souadabscook Str,Reach           , 3
Up Type= 3
Up Slope=0.001667
Dn Type= 3
Dn Slope=0.00262
Boundary for River Rch & Prof#=Souadabscook Str,Reach           , 4
Up Type= 3
Up Slope=0.001667
Dn Type= 3
Dn Slope=0.00262
DSS Import GetInterval= 0
DSS Import GetPeak= 0
DSS Import FillOption= 0

--- HampdenBridges.f01 (steady flow) ---

Flow Title=FEMA 1987 FIS FLOWS
Program Version=5.03
Number of Profiles= 4
Profile Names=10 year,50 year,100 year,500 year
River Rch & RM=Souadabscook Str,Reach           ,41522.56
    3090    4380    4880    6190
Boundary for River Rch & Prof#=Souadabscook Str,Reach           , 1
Up Type= 3
Up Slope=0.001667
Dn Type= 1
Dn Known WS=121.95
Boundary for River Rch & Prof#=Souadabscook Str,Reach           , 2
Up Type= 3
Up Slope=0.001667
Dn Type= 1
Dn Known WS=123.45
Boundary for River Rch & Prof#=Souadabscook Str,Reach           , 3
Up Type= 3
Up Slope=0.001667
Dn Type= 1
Dn Known WS=124.05
Boundary for River Rch & Prof#=Souadabscook Str,Reach           , 4
Up Type= 3
Up Slope=0.001667
Dn Type= 1
Dn Known WS=125.35
DSS Import GetInterval= 0
DSS Import GetPeak= 0
DSS Import FillOption= 0

--- HampdenBridges.g01 (geometry) ---

Geom Title=Hampden Bridges Existing
Program Version=5.03

River Reach=Souadabscook Str,Reach
Reach XY= 30
1682815.70056407 455246.817264551683399.99559546 455041.67040697
1683552.68363948 454823.006610751683949.34990444 453544.63460544
1683845.00119331 453475.614245431683567.32750438 453666.74755007
1683436.44945991 453611.885212621683408.15150435 453427.83091927
1683612.98006549 453182.167105861683812.47907307 452732.74074725
 1684183.8897398 452528.334296461684443.87720652 452515.94602672
 1685920.1477548 452848.679308711686523.69008824 453137.14901848
1686501.58231046 453781.670873861686642.18777715 454211.27837108
1687476.91430111 454870.700913151687963.85389802 454922.02374495
1688204.82867584 455161.382813951688332.16947587 455136.60627446
  1688436.518187 454833.978542121688542.63552035 454858.75508161
1688652.29009815 455237.482185231688869.83063152 455515.33337808
1688882.21098708 456134.746865321689191.71987602  456150.6746407
1689352.66449827 456035.64070736 1689785.9769428 455336.58834319
1690103.00247619 455210.935892921690841.41607147 453277.06262344

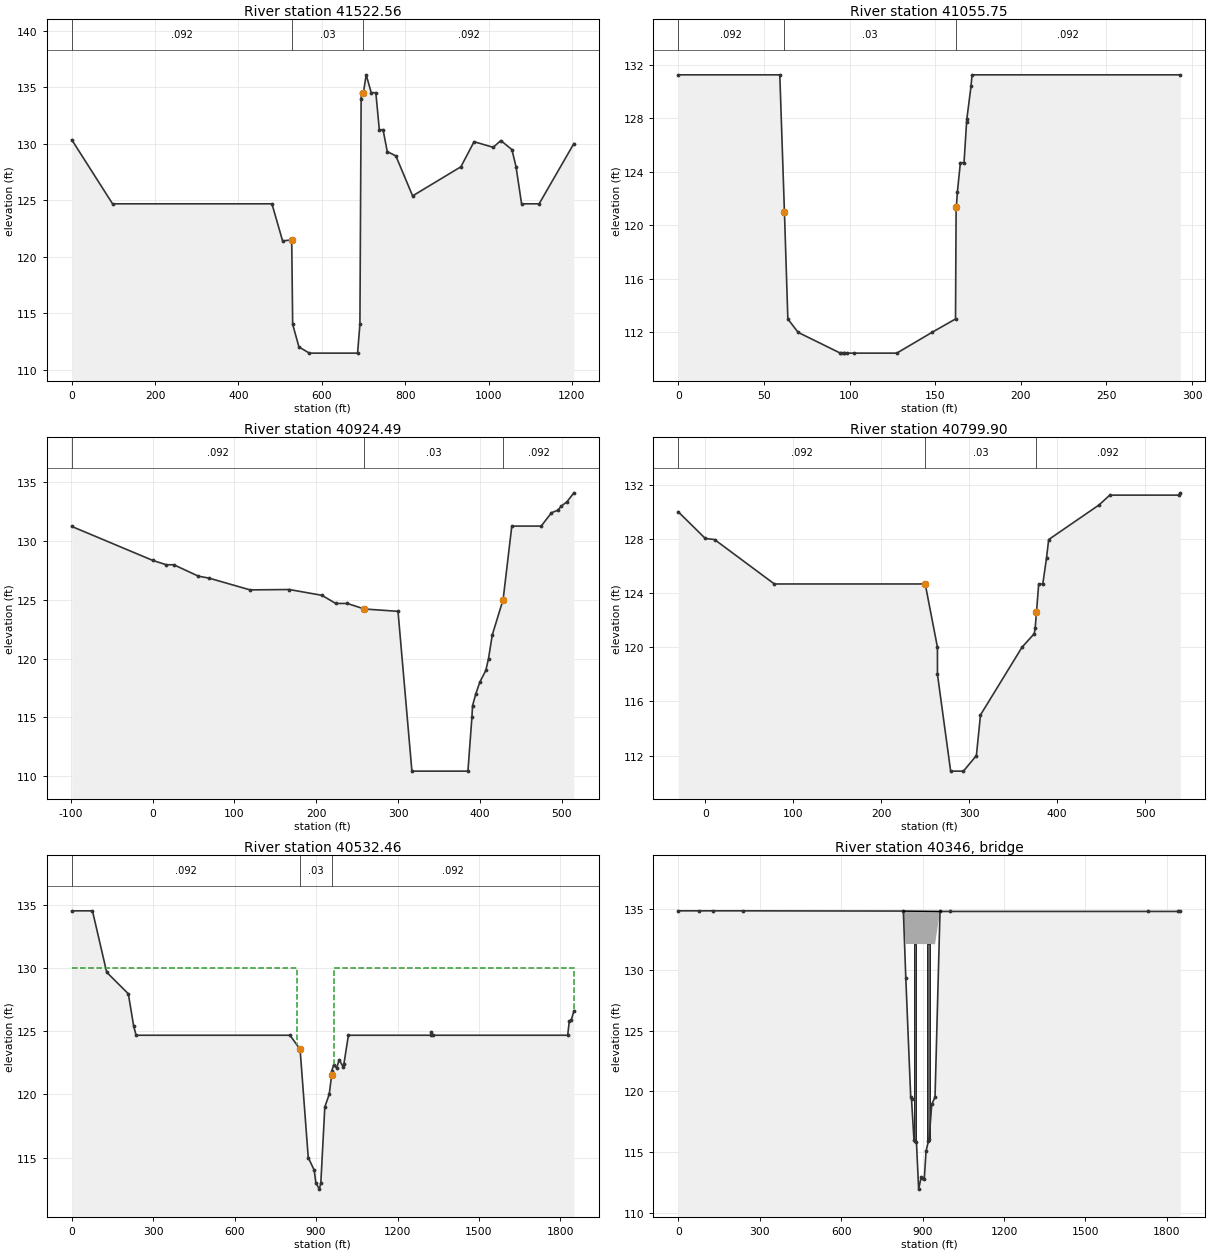
Type RM Length L Ch R = 1 ,41522.56,491.52,466.81,500.23
XS GIS Cut Line= 3
1684022.62809906 455276.803504011683281.48689788 454759.91122281
1683076.88942547  454685.4632693
#Sta/Elev= 30
       0  130.34   97.88  124.67  480.24  124.67  505.79  121.39  527.68  121.47
     530     114     545     112     570  111.45   685.7  111.45  691.33     114
  694.24  133.93  694.93  134.51   699.7  134.51  706.42  136.09  718.46  134.51
  729.53  134.51  737.87  131.23  746.86  131.23  756.91   129.3  777.62  128.91
  817.75  125.37  933.64  127.95  965.26  130.17 1011.04  129.67 1029.43  130.27
 1056.02  129.47 1065.89  127.95 1079.19  124.67 1121.31  124.67 1204.59     130
#Mann= 3 , 0 , 0
       0    .092       0  527.68     .03       0   699.7    .092       0
Bank Sta=527.68,699.7
XS Rating Curve= 0 ,0
Exp/Cntr=0.3,0.1

Type RM Length L Ch R = 1 ,41055.75,139.32,131.26,133.34
XS GIS Cut Line= 2
1683743.61619896 454510.536871981683467.43937107 454412.29124599
#Sta/Elev= 24
       0  131.23    59.3  131.23      62     121      64     113      70     112
   94.64  110.45      95  110.45   96.86  110.45   96.93  110.45   98.34  110.45
  102.77  110.45   127.6  110.45  148.14     112  161.89     113  162.24  121.39
  162.39  121.39  162.97  122.47  164.73  124.67  166.86  124.67  168.34  127.68
  168.52  127.95  170.92  130.36  171.55  131.23  293.13  131.23
#Mann= 3 , 0 , 0
       0    .092       0      62     .03       0  162.24    .092       0
Bank Sta=62,162.24
XS Rating Curve= 0 ,0
Exp/Cntr=0.3,0.1

Type RM Length L Ch R = 1 ,40924.49,124.28,124.6,124.95
XS GIS Cut Line= 3
1684046.31000267454495.1396858031683954.29578272 454458.61047383
1683475.58989971 454268.56649277
#Sta/Elev= 30
     -99   131.2       0  128.32   16.66  127.95   25.76  127.95   55.98  126.98
   68.73  126.82  119.03  125.82     167  125.85  206.91  125.36  223.82  124.67
  237.84  124.67  258.79   124.2     300     124     317  110.45  385.52  110.45
  390.36     115  391.16     116  395.12     117  400.09     118  407.43     119
  410.69     120  415.29     122  428.55     125  439.17  131.23   475.1  131.23
  487.69  132.36  495.65  132.58  499.45  132.91  506.64  133.29  515.05  134.05
#Mann= 3 , 0 , 0
     -99    .092       0  258.79     .03       0  428.55    .092       0
Bank Sta=258.79,428.55
XS Rating Curve= 0 ,0
Exp/Cntr=0.3,0.1

Type RM Length L Ch R = 1 ,40799.90,237.36,267.44,303.63
XS GIS Cut Line= 2
1684005.86197501 454343.61337021 1683503.0135125 454146.68849768
#Sta/Elev= 23
  -30.78     130       0  128.03   10.51  127.95   78.51  124.67     250  124.67
  263.91     120  263.93     118  278.92  110.85  293.47  110.85   308.2     112
  312.86     115  360.08     120  373.96     121  375.01  121.39  376.52   122.6
  379.03  124.67  383.69  124.67  387.92  126.59  390.38  127.95  447.53   130.5
  459.87  131.23  538.04  131.23  540.03   131.4
#Mann= 3 , 0 , 0
  -30.78    .092       0     250     .03       0  376.52    .092       0
Bank Sta=250,376.52
XS Rating Curve= 0 ,0
Exp/Cntr=0.3,0.1

Type RM Length L Ch R = 1 ,40532.46,353.3,338.74,328.11
XS GIS Cut Line= 2
1684697.53787277 453762.189907721682905.92356134 454220.55588828
#Sta/Elev= 30
       0  134.51   76.18  134.51   128.7  129.65  208.29  127.95     228   125.4
  236.85  124.67  803.64  124.67     841  123.56     871     115     893     114
     899     113     912   112.5  917.41     113  932.05     119  948.31     120
  957.02  121.49  957.93  121.87  964.71  122.31  975.59  122.09  985.05  122.73
  999.18  122.18 1002.18  122.37 1018.94  124.67 1322.13  124.67 1323.96  124.89
 1329.22  124.67  1826.6  124.67 1832.48  125.76 1840.14  125.89 1849.32  126.58
#Mann= 3 , 0 , 0
       0    .092       0     841     .03       0  957.02    .092       0
#XS Ineff= 2 , 0
       0     829     130     965       0     130
Permanent Ineff=
       F       F
Bank Sta=841,957.02
XS Rating Curve= 0 ,0
Exp/Cntr=0.5,0.3

Type RM Length L Ch R = 3 ,40346   ,,,
Bridge Culvert--1,0,-1,-1, 0
Deck Dist Width WeirC Skew NumUp NumDn MinLoCord MaxHiCord MaxSubmerge Is_Ogee
62.5,182,2.6,0, 2, 2, , , 0.98, 0, 0,0,,
  829.83  969.22
  134.83   134.8
  132.13   132.1
  397.24   532.1
  134.83   134.8
  132.13   132.1
Pier Skew, UpSta & Num, DnSta & Num=  ,871.4, 4 ,439.58, 4 , 0 , 0 , 0 ,,
     8.5     8.5 4.45833       3
     108   114.5   114.5     135
     8.5     8.5 4.45833       3
     108   114.5   114.5     135
Pier Skew, UpSta & Num, DnSta & Num=  ,921.4, 4 ,489.58, 4 , 0 , 0 , 0 ,,
     8.5     8.5   4.458       3
     108   114.5   114.5     135
     8.5     8.5   4.458       3
     108   114.5   114.5     135
BR Coef=-1 , 1 , 1 ,1.05, 0 ,,,0.8,-1,1.6,0,
WSPro=,,,, 1 ,,,, 0 ,,,, 0 ,,,,-1 ,-1 ,-1 , 0 , 0 , 0 , 0 , 0
BR U #Sta/Elev= 25
       0  134.85   76.18  134.85   128.7  134.85  236.85  134.85  829.23  134.83
  838.23  129.31   856.3  119.54   859.3  119.36  868.31  116.01  871.44  115.94
  877.35  115.88  885.52  111.97  894.83  112.95     899   112.9  906.28   112.8
  912.81  115.09  921.39  115.91  924.27  116.11   933.7  118.93  945.87  119.54
  964.22   134.8 1000.52   134.8  1729.9   134.8 1841.82   134.8 1849.32   134.8
BR U #Mann= 3
       0    .092   856.3     .03  964.22    .092
BR U Banks=856.3,945.87
BR D #Sta/Elev= 30
       0   134.9   49.93   134.9   145.4   134.9  252.88   134.9   330.7   134.9
  397.24   134.9  418.73  122.55   419.5  122.36     424  119.54  424.94  119.27
  430.81  116.96  439.61  115.34  441.33  114.94  447.05   112.9  467.33   112.9
  468.88  113.48  476.45  116.27  485.21  116.47  489.55  116.47  514.88  119.65
  521.47  124.58   532.1  134.99  585.48  134.99  642.52  134.99  823.15  134.99
  953.98  134.99 1075.68  134.99 1538.67  134.99 1568.57  134.99 1573.63  134.99
BR D #Mann= 3
       0    .092  424.94     .03  521.47    .092
BR D Banks=424.94,514.88
BC Design=,, 0 ,, 0 ,,,,,,
BC Use User HTab Curves=0
BC User HTab FreeFlow(D)= 0

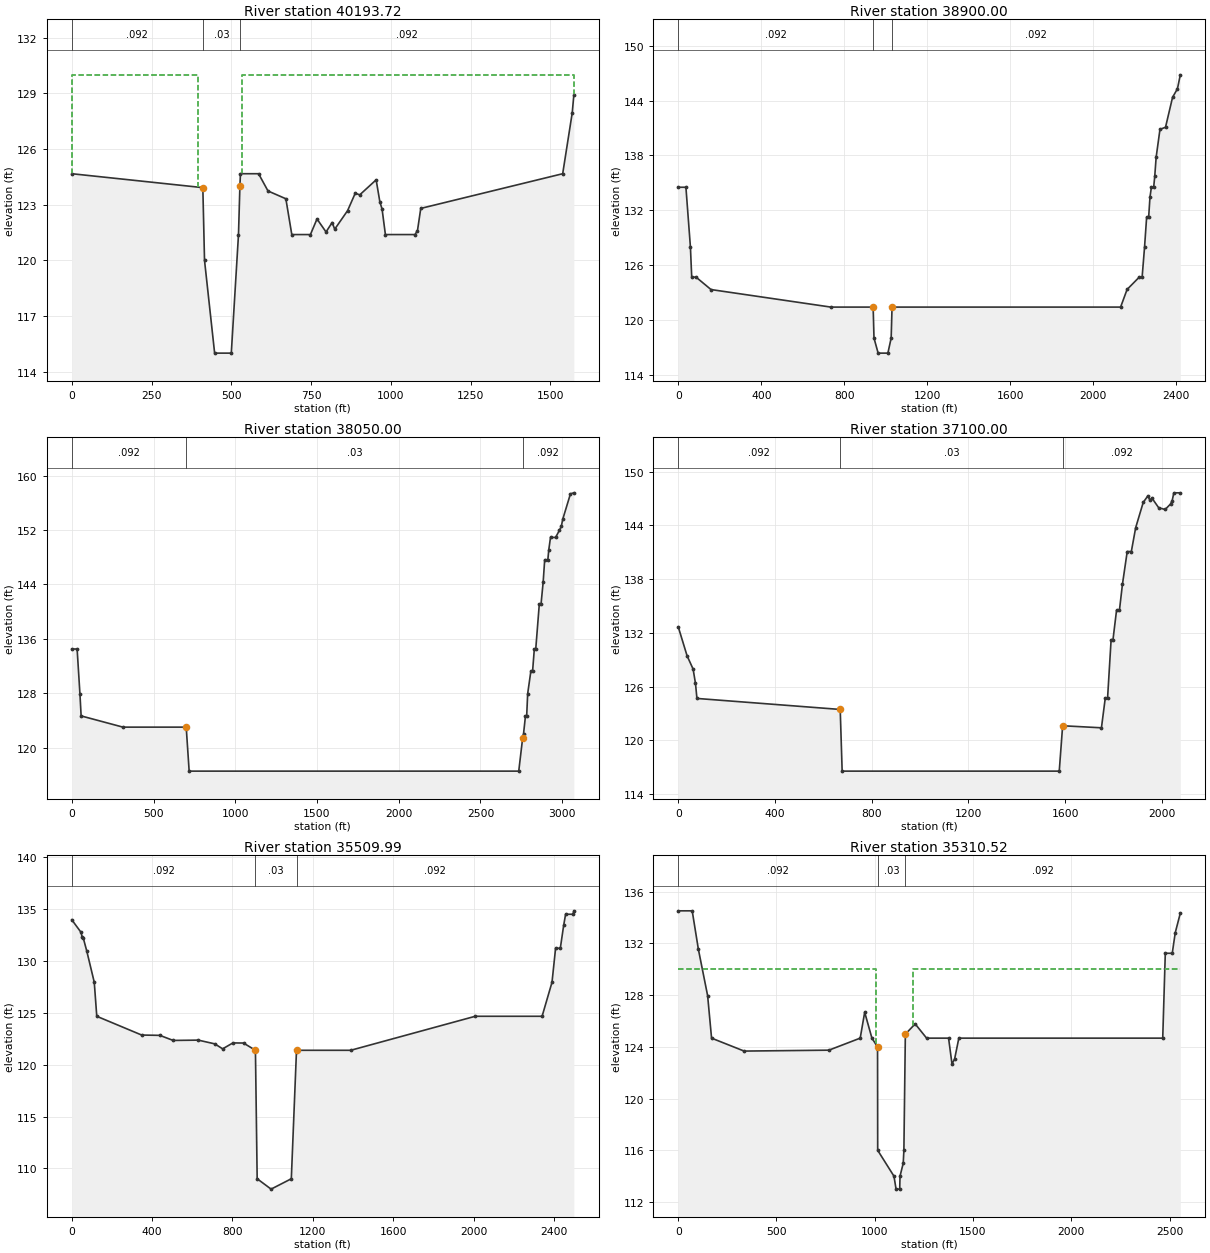
Type RM Length L Ch R = 1 ,40193.72,1334.06,1293.72,1289.57
XS GIS Cut Line= 2
1684384.02689168 453566.950169551682847.89064466 453908.41573453
#Sta/Elev= 30
       0  124.67   410.8  123.92  416.07     120  447.76     115     500     115
  522.55  121.39  526.97     124   528.7  124.67  585.48  124.67  615.02  123.74
  671.02  123.32  689.62  121.39  747.98  121.39  768.61  122.23  796.94  121.53
  816.09  122.04  824.14  121.68   864.5  122.68  888.53  123.62  902.51  123.53
  953.98  124.34  965.79  123.14  972.55  122.77  982.97  121.39 1075.68  121.39
  1083.5   121.6 1093.84   122.8 1538.67  124.67 1568.57  127.95 1573.63  128.92
#Mann= 3 , 0 , 0
       0    .092       0   410.8     .03       0  526.97    .092       0
#XS Ineff= 2 , 0
       0     397     130     532       0     130
Permanent Ineff=
       F       F
Bank Sta=410.8,526.97
XS Rating Curve= 0 ,0
Exp/Cntr=0.5,0.3

Type RM Length L Ch R = 1 ,38900.00,1980.39,850,700.36
XS GIS Cut Line= 4
1684411.60053094 453639.284732491684336.93811333 453443.42109278
1684335.70237668 453446.480987371682290.37439571 452620.47646901
#Sta/Elev= 30
       0  134.51   37.01  134.51   58.73  127.95   64.91  124.67   85.79  124.67
  157.86  123.31   735.2  121.39     939  121.39  943.06     118     963  116.35
    1010  116.35 1025.78     118    1030  121.39 2131.11  121.39 2162.29  123.32
 2220.96  124.67 2234.78  124.67 2246.45  127.95 2256.48  131.23 2266.23  131.23
 2272.57  133.42 2279.36  134.51 2290.38  134.51 2295.58   135.7 2302.33   137.8
 2320.72  140.85 2347.45  141.08 2381.42  144.36 2404.91  145.29 2418.73  146.82
#Mann= 3 , 0 , 0
       0    .092       0     939     .03       0    1030    .092       0
Bank Sta=939,1030
XS Rating Curve= 0 ,0
Exp/Cntr=0.3,0.1

Type RM Length L Ch R = 1 ,38050.00,4125.81,950,762.57
XS GIS Cut Line= 3
1684540.19140436 453598.652501121684049.89397695 452312.44396731
1682478.66373937 451677.90354754
#Sta/Elev= 30
       0  134.51   32.73  134.51   49.85  127.95   57.21  124.67     313  123.02
     700  123.02     718  116.55    2734  116.55 2757.77  121.39 2763.45  122.06
 2775.11  124.67 2782.53  124.67 2788.64  127.95 2807.97  131.23 2818.58  131.23
 2829.28  134.51 2838.02  134.51 2859.61  141.08  2870.2  141.08 2883.41  144.36
 2892.69  147.64    2912  147.64 2917.63  149.09 2928.27  150.92 2959.31  150.92
 2982.26  151.94 2994.45  152.55 3002.69  153.56 3050.21  157.33 3071.01  157.48
#Mann= 3 , 0 , 0
       0    .092       0     700     .03       0 2757.77    .092       0
Bank Sta=700,2757.77
XS Rating Curve= 0 ,0
Exp/Cntr=0.3,0.1

Type RM Length L Ch R = 1 ,37100.00,2226.36,1590,1541.38
XS GIS Cut Line= 2
1684802.17321938 453479.955161311685438.29431726 451503.03744968
#Sta/Elev= 30
       0  132.67   36.62  129.43   61.52  127.95   71.35  126.35   77.34  124.67
     670  123.44     678  116.55    1576  116.55    1590  121.62 1750.52  121.39
 1766.12  124.67 1775.78  124.67 1790.51  131.23 1798.26  131.23 1812.94  134.51
 1824.88  134.51 1837.47  137.44 1857.13  141.08 1874.17  141.08 1892.05  143.74
 1923.23  146.56 1942.94  147.32 1950.17  146.84 1959.82  147.04 1987.34  145.97
 2014.15  145.78 2036.29  146.39 2043.16  146.77 2049.91  147.64 2076.74  147.64
#Mann= 3 , 0 , 0
       0    .092       0     670     .03       0    1590    .092       0
Bank Sta=670,1590
XS Rating Curve= 0 ,0
Exp/Cntr=0.3,0.1

Type RM Length L Ch R = 1 ,35509.99,238.86,199.47,180.1
XS GIS Cut Line= 6
1685499.39494739 453197.062740261686298.46332961 453249.78462718
1686298.84539871 453251.004388811686850.60578023 453078.17504952
1686850.22371112 453076.955287891687787.48558086 452467.54520197
#Sta/Elev= 30
       0  133.98   45.18  132.79   52.67  132.27   57.81  132.18   74.96  130.94
     112  127.95  124.47  124.67  348.02  122.86  438.43  122.83  504.89  122.34
  629.89  122.37  711.77  122.01  751.16  121.53  802.08   122.1  854.95  122.09
  914.35  121.39     923     109  992.31     108    1093     109 1118.79  121.39
 1388.81  121.39 2008.59  124.67 2341.48  124.67 2390.81  127.95 2408.61  131.23
 2432.16  131.23 2448.79  133.43 2458.49  134.51 2495.51  134.51 2499.52  134.84
#Mann= 3 , 0 , 0
       0    .092       0  914.35     .03       0 1118.79    .092       0
Bank Sta=914.35,1118.79
XS Rating Curve= 0 ,0
Exp/Cntr=0.3,0.1

Type RM Length L Ch R = 1 ,35310.52,323.86,323.41,324.51
XS GIS Cut Line= 2
1685486.26442768 453239.401764221688021.64576052  453555.1299972
#Sta/Elev= 30
       0  134.51   71.06  134.51   102.6  131.53  149.59  127.95  169.59  124.67
  335.28  123.67  766.63  123.74  925.99  124.67  948.82  126.67  985.61  124.67
 1014.27  123.99    1015     116 1097.86     114 1108.47     113 1127.07     113
 1128.57     114 1144.94     115 1148.31     116 1155.77  124.98 1205.72  125.77
 1263.86  124.67 1375.69  124.67 1393.12  122.67 1406.45  123.06 1427.97  124.67
 2465.49  124.67 2478.55  131.23 2513.93  131.23 2529.23  132.82 2554.96  134.33
#Mann= 3 , 0 , 0
       0    .092       0 1014.27     .03       0 1155.77    .092       0
#XS Ineff= 2 , 0
       0    1004     130    1195       0     130
Permanent Ineff=
       F       F
Bank Sta=1014.27,1155.77
XS Rating Curve= 0 ,0
Exp/Cntr=0.5,0.3

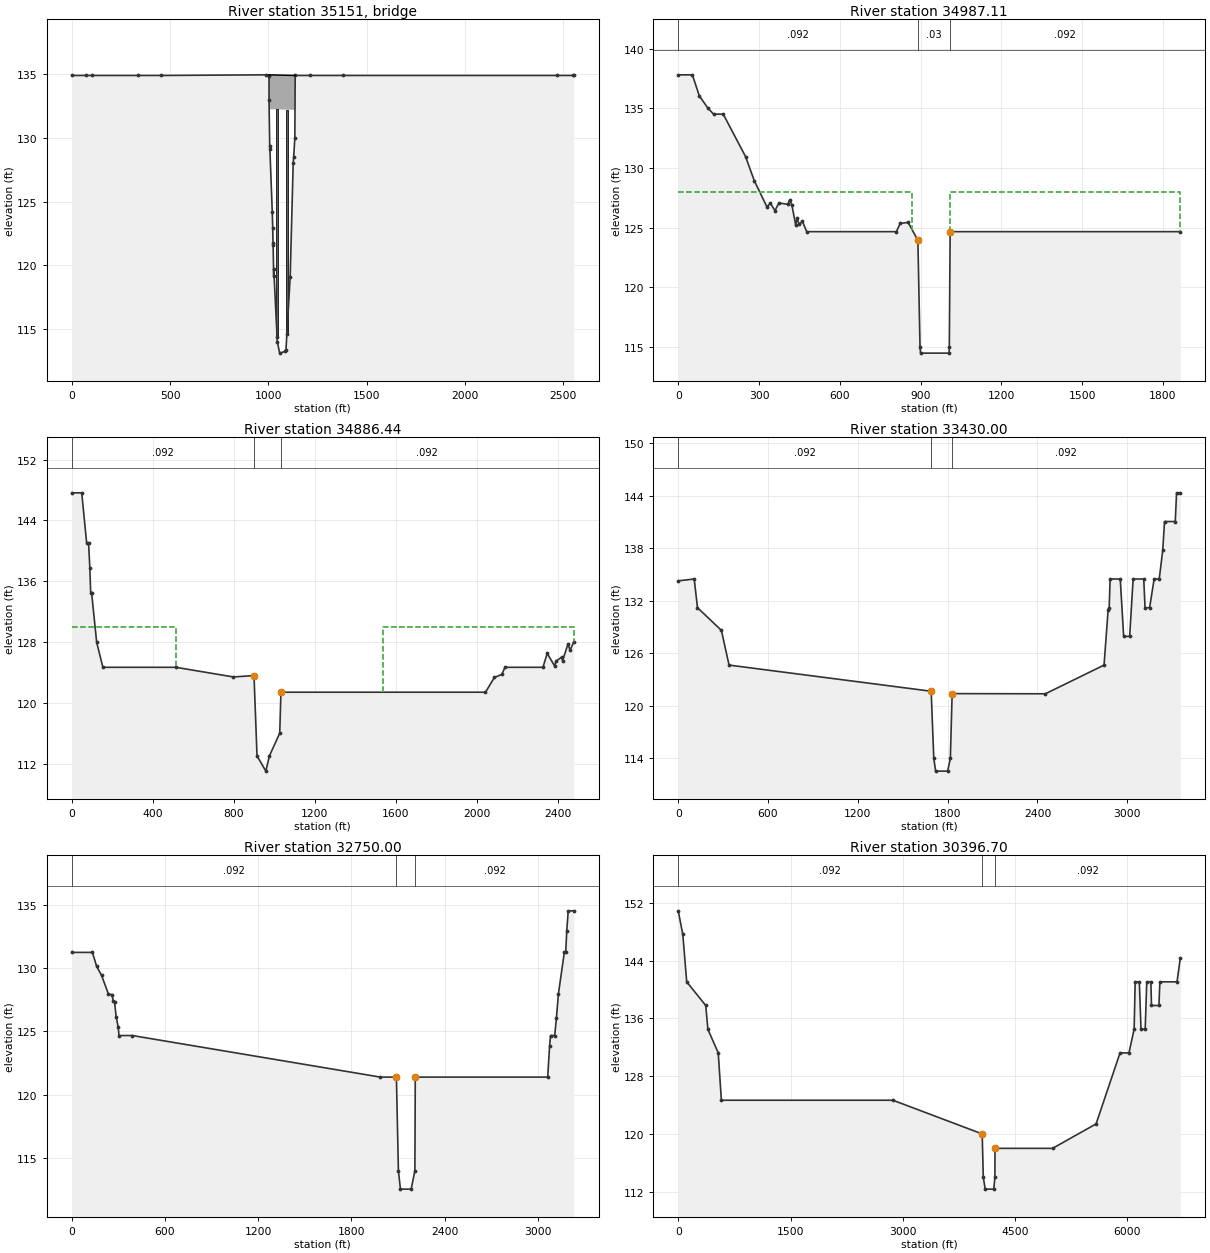
Type RM Length L Ch R = 3 ,35151   ,,,
Bridge Culvert--1,0,-1,-1, 0
Deck Dist Width WeirC Skew NumUp NumDn MinLoCord MaxHiCord MaxSubmerge Is_Ogee
59,201,2.6,0, 2, 2, , , 0.98, 0, 0,0,,
 1002.19    1137
  134.95   134.9
  132.25   132.2
  869.62  1006.6
  134.95   134.9
  132.25   132.2
Pier Skew, UpSta & Num, DnSta & Num=  ,1044.72, 4 ,918.6, 4 , 0 , 0 , 0 ,,
     8.5     8.5     4.5       3
     108   114.5   114.5   134.9
     8.5     8.5     4.5       3
     108   114.5   114.5   134.9
Pier Skew, UpSta & Num, DnSta & Num=  ,1094.72, 4 ,968.6, 4 , 0 , 0 , 0 ,,
     8.5     8.5     4.5       3
     108   114.5   114.5   134.9
     8.5     8.5     4.5       3
     108   114.5   114.5   134.9
BR Coef=-1 , 1 , 1 ,1.05, 0 ,,,0.8,-1,1.6,0,
WSPro=,,,, 1 ,,,, 0 ,,,, 0 ,,,,-1 ,-1 ,-1 , 0 , 0 , 0 , 0 , 0
BR U #Sta/Elev= 32
       0   134.9   71.06   134.9   102.6   134.9  335.28   134.9  453.98   134.9
  990.31  134.95 1003.64  134.84  1003.8  132.95 1007.33  129.34  1008.1  129.14
 1020.29  124.18 1022.57  122.93 1024.04  121.75 1024.54   121.6  1027.6  119.15
 1027.87  119.72  1044.7  114.38 1046.45  113.96 1058.16  113.11    1085  113.24
    1090  113.33  1094.7  114.65 1111.53  119.11 1126.75     128 1129.23   128.5
 1135.14  129.97    1137   134.9 1211.26   134.9 1381.88   134.9 2470.65   134.9
 2549.63   134.9 2554.96   134.9
BR U #Mann= 3
       0    .092  1027.6  .03092 1126.75    .092
BR U Banks=1027.6,1111.53
BR D #Sta/Elev= 38
       0  134.95   52.49  134.95   78.43  134.95  256.76  134.95  322.72  134.95
  324.23  134.95  723.42  134.95  819.43  134.95  869.67  134.95  871.63  134.92
  873.72  129.48  874.69  129.42  879.99  128.21  880.85  128.25  886.93  124.81
   899.5  121.61  901.86  119.05     912  113.95  914.14  114.12   917.5  114.45
  923.78  112.79  930.74  113.25  942.05  113.18   949.9  112.85  952.62   112.8
  964.09  113.27  964.21  113.28  969.66  117.07  975.36  117.59  978.17  119.26
 1002.76  129.94 1004.37  130.23  1006.6  134.92  1009.8  134.95 1233.58     135
 1241.08     135  1250.2     135 1864.66     135
BR D #Mann= 3
       0    .092  901.86     .03 1002.76    .092
BR D Banks=901.86,978.17
BC Design=,, 0 ,, 0 ,,,,,,
BC Use User HTab Curves=0
BC User HTab FreeFlow(D)= 0

Type RM Length L Ch R = 1 ,34987.11,102.26,100.67,100.66
XS GIS Cut Line= 3
1685549.50731871 453595.550636771686930.88895904 453734.31079906
 1687398.6468077 453824.25805382
#Sta/Elev= 30
       0   137.8   52.49   137.8   78.43  136.03  110.67     135  131.24  134.51
  167.05  134.51  250.16  130.95  282.14  128.95  329.32  126.75  342.51  127.04
  359.23  126.43  373.71  127.07  406.48  126.96   413.8  127.32  421.68  126.94
  436.33  125.22  441.45  125.78  449.26  125.27  461.24  125.53  477.18  124.67
  810.01  124.67   824.5  125.36  853.94  125.44     890  123.94     898     115
     900   114.5 1005.68   114.5 1006.77     115  1009.8  124.67 1864.66  124.67
#Mann= 3 , 0 , 0
       0    .092       0     890     .03       0  1009.8    .092       0
#XS Ineff= 2 , 0
       0     870     128    1010       0     128
Permanent Ineff=
       F       F
Bank Sta=890,1009.8
XS Rating Curve= 0 ,0
Exp/Cntr=0.5,0.3

Type RM Length L Ch R = 1 ,34886.44,1434.58,1456.45,1510.58
XS GIS Cut Line= 2
1685539.51258959 453695.049910091688006.72683104 453942.88225311
#Sta/Elev= 30
       0  147.64   49.23  147.64   73.34  141.08      83  141.08   89.13   137.8
   93.38  134.51   97.76  134.51  123.03  127.95  153.67  124.67  513.67  124.67
  798.24   123.4     900  123.58  914.94     113  958.56     111  976.01     113
 1027.06     116 1033.12  121.39 2043.25  121.39  2087.2  123.33 2123.78  123.73
 2139.48  124.67 2327.13  124.67 2348.14   126.5 2384.41  124.86 2392.28  125.49
 2419.71  126.01 2423.61  125.51 2450.42  127.72 2461.16  126.94 2479.63  128.01
#Mann= 3 , 0 , 0
       0    .092       0     900     .03       0 1033.12    .092       0
#XS Ineff= 2 , 0
       0     513     130 1539.19       0     130
Permanent Ineff=
       F       F
Bank Sta=900,1033.12
XS Rating Curve= 0 ,0
Exp/Cntr=0.3,0.1

Type RM Length L Ch R = 1 ,33430.00,705.66,680,677.22
XS GIS Cut Line= 2
1686280.26900402 456162.143845761688446.00242304 453600.34248847
#Sta/Elev= 30
       0   134.3  106.82  134.51  128.59  131.23  288.35  128.64  339.61  124.67
    1690  121.68 1707.48     114    1720  112.55    1800  112.55 1818.14     114
    1830  121.41 2452.94  121.39 2845.03  124.67 2872.45  131.01 2879.27  131.23
 2885.62  134.51 2953.32  134.51 2976.01  127.95 3016.17  127.95 3039.38  134.51
 3110.37  134.51 3118.88  131.23 3149.54  131.23 3179.57  134.51 3213.71  134.51
  3237.3   137.8 3248.96  141.08 3320.81  141.08 3329.56  144.36 3354.58  144.36
#Mann= 3 , 0 , 0
       0    .092       0    1690     .03       0    1830    .092       0
Bank Sta=1690,1830
XS Rating Curve= 0 ,0
Exp/Cntr=0.3,0.1

Type RM Length L Ch R = 1 ,32750.00,2290.9,2353.3,2445.53
XS GIS Cut Line= 2
1686495.72922987 456496.894013591688803.78183282 454233.83624103
#Sta/Elev= 30
       0  131.23  133.08  131.23  160.24  130.12  191.68  129.42  235.81  127.95
  258.38   127.9  267.13  127.43  275.31  127.31  285.77  126.16  298.78  125.34
  304.16  124.67   389.4  124.67 1986.66  121.39    2090  121.39    2103     114
    2116  112.55    2185  112.55    2209     114 2211.62  121.39 3063.92  121.39
 3076.59  123.88 3082.33  124.67 3109.28  124.67 3120.55  126.09 3133.01  127.95
 3171.06  131.23 3180.02  131.23 3186.89  132.93 3196.06  134.51 3232.42  134.51
#Mann= 3 , 0 , 0
       0    .092       0    2090     .03       0 2211.62    .092       0
Bank Sta=2090,2211.62
XS Rating Curve= 0 ,0
Exp/Cntr=0.3,0.1

Type RM Length L Ch R = 1 ,30396.70,831.69,912.73,1022
XS GIS Cut Line= 2
1688504.66525903 460289.106422011689307.48245068  453631.0865293
#Sta/Elev= 30
       0  150.92   61.17  147.64  113.03  141.08  367.48   137.8  395.76  134.51
  534.27  131.23  576.17  124.67 2867.45  124.67    4060     120 4074.71     114
    4100  112.35    4215  112.35 4229.63     114    4231     118    5000     118
 5581.33  121.39 5901.09  131.23 6020.29  131.23 6089.46  134.51 6103.48  141.08
 6158.82  141.08 6181.26  134.51 6237.16  134.51 6258.09  141.08 6313.23  141.08
 6321.13   137.8 6420.66   137.8 6433.33  141.08 6662.41  141.08 6706.25  144.36
#Mann= 3 , 0 , 0
       0    .092       0    4060     .03       0    4231    .092       0
Bank Sta=4060,4231
XS Rating Curve= 0 ,0
Exp/Cntr=0.3,0.1

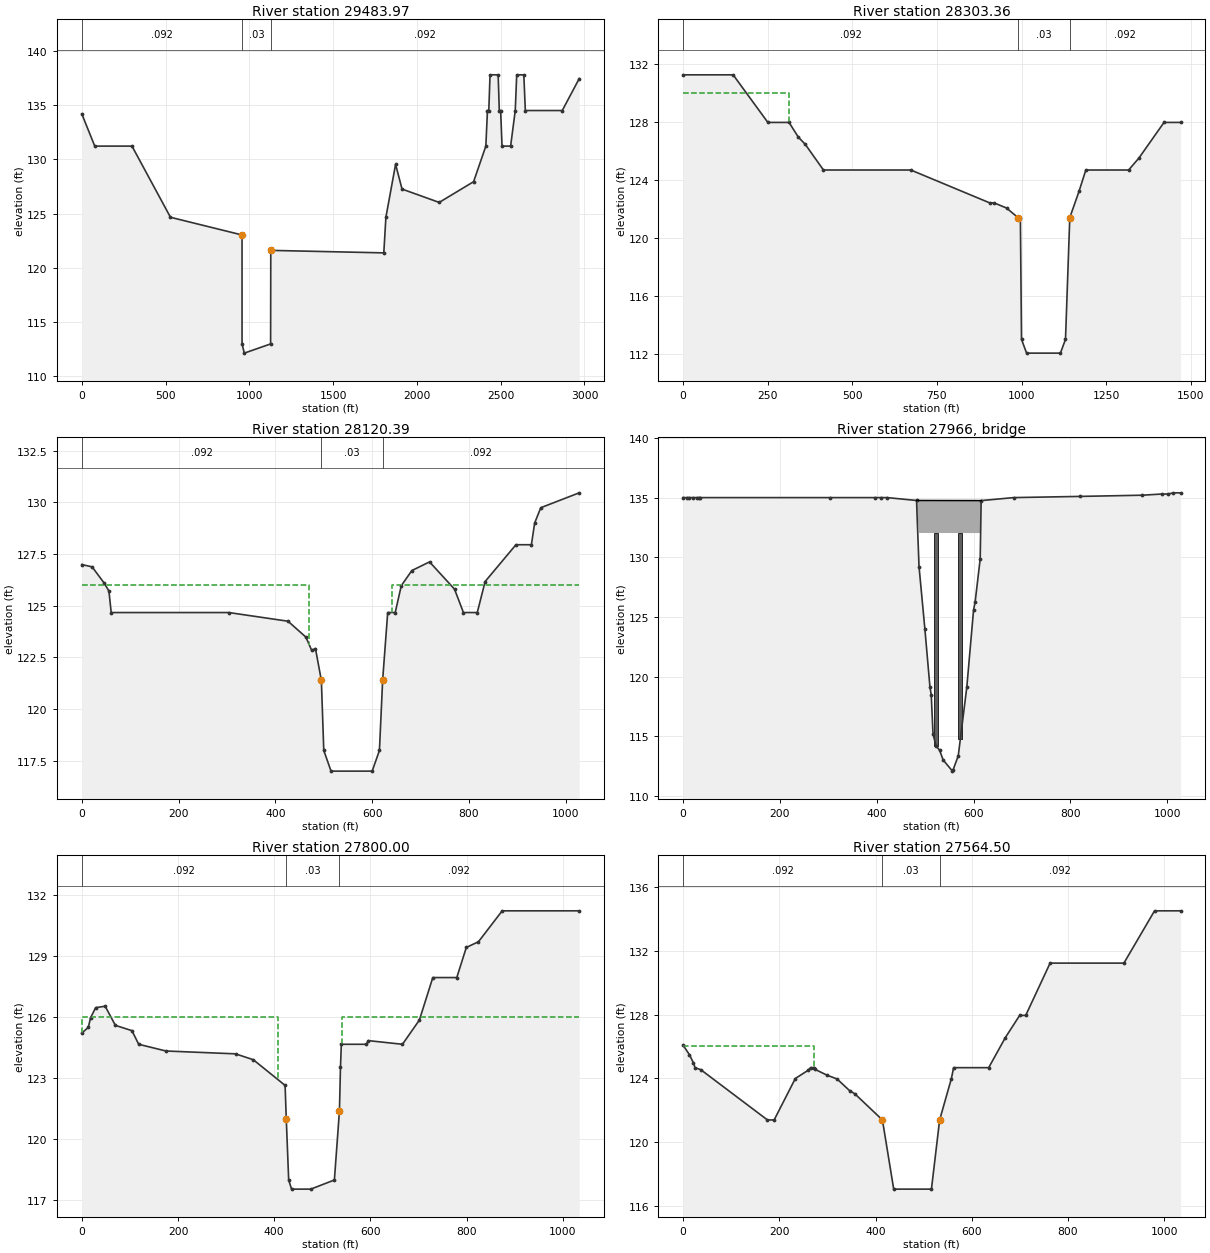
Type RM Length L Ch R = 1 ,29483.97,1179.44,1180.61,1189.53
XS GIS Cut Line= 3
1690487.05088739 456103.867857941689379.23424103 455442.78396401
1689786.13722257 453814.13158106
#Sta/Elev= 30
       0   134.2   77.44  131.23  299.56  131.23  529.37  124.67   956.5  123.04
  956.54     113     970  112.15    1127     113    1128  121.62 1802.56  121.39
 1815.06  124.67 1872.87  129.55 1911.38  127.27 2133.17  126.04 2338.41  127.95
 2411.61  131.23 2421.21  134.51  2429.2  134.51 2436.65   137.8 2485.07   137.8
 2491.84  134.51 2499.85  134.51 2508.18  131.23  2559.5  131.23 2587.13  134.51
 2595.82   137.8  2638.3   137.8 2647.23  134.51 2867.67  134.51 2968.79  137.45
#Mann= 3 , 0 , 0
       0    .092       0   956.5     .03       0    1128    .092       0
Bank Sta=956.5,1128
XS Rating Curve= 0 ,0
Exp/Cntr=0.3,0.1

Type RM Length L Ch R = 1 ,28303.36,197.98,182.97,196.3
XS GIS Cut Line= 2
1691270.61087973 454958.163775571689844.78733432 454600.54073495
#Sta/Elev= 24
       0  131.23  147.79  131.23  250.38  127.95  312.95  127.95  340.41  126.94
  361.27  126.43  414.66  124.67   672.9  124.67  905.51  122.41  919.53   122.4
  955.76  122.05  989.59  121.39  996.65  121.39    1000     113    1015  112.05
    1115  112.05    1130     113 1142.69  121.39 1169.85  123.19 1190.06  124.67
 1316.58  124.67 1346.83  125.49 1421.15  127.95 1469.99  127.95
#Mann= 3 , 0 , 0
       0    .092       0  989.59     .03       0 1142.69    .092       0
#XS Ineff= 2 , 0
       0  312.95     130               0
Permanent Ineff=
       F       F
Bank Sta=989.59,1142.69
XS Rating Curve= 0 ,0
Exp/Cntr=0.3,0.1

Type RM Length L Ch R = 1 ,28120.39,323.53,320.39,351.2
XS GIS Cut Line= 2
1690878.72756888 454678.193318111689881.85678236 454428.15960046
#Sta/Elev= 30
       0  126.99   21.32  126.88   46.38  126.09   56.08  125.71   60.76  124.67
  303.76  124.67  426.12  124.25   463.1  123.48  474.98  122.84  482.79  122.93
  494.99  121.39     500     118     515     117     600     117     615     118
 621.599  121.39  632.07  124.67  647.63  124.67  660.15  125.97  681.96   126.7
   718.5  127.12  770.15   125.8  788.55  124.67  817.14  124.67  833.37  126.17
  897.05  127.95  928.99  127.95   935.7     129  948.37  129.74 1027.75  130.46
#Mann= 3 , 0 , 0
       0    .092       0  494.99     .03       0 621.599    .092       0
#XS Ineff= 2 , 0
       0     470     126     640       0     126
Permanent Ineff=
       F       F
Bank Sta=494.99,621.599
XS Rating Curve= 0 ,0
Exp/Cntr=0.3,0.1

Type RM Length L Ch R = 3 ,27966   ,,,
Bridge Culvert--1,0,-1,-1, 0
Deck Dist Width WeirC Skew NumUp NumDn MinLoCord MaxHiCord MaxSubmerge Is_Ogee
45,212,2.6,0, 2, 2, , , 0.98, 0, 0,0,,
  482.29   615.8
  134.76  134.75
  132.04  132.03
   406.7   541.6
   134.9   134.9
  132.18  132.18
Pier Skew, UpSta & Num, DnSta & Num=  ,522.45, 4 ,449.17, 4 , 0 , 0 , 0 ,,
   8.104   8.104   8.104       3
     113     113     119  132.04
   8.104   8.104   8.104       3
     113     113     119  132.18
Pier Skew, UpSta & Num, DnSta & Num=  ,572.87, 4 ,499.2, 4 , 0 , 0 , 0 ,,
   8.104   8.104   8.104       3
     113     113     119  132.04
   8.104   8.104   8.104       3
     113     113     119  132.18
BR Coef=-1 , 1 , 1 ,1.05, 0 ,,,0.8,-1,1.6,0,
WSPro=,,,, 1 ,,,, 0 ,,,, 0 ,,,,-1 ,-1 ,-1 , 0 , 0 , 0 , 0 , 0
BR U #Sta/Elev= 35
       0     135    8.62     135   11.84     135   21.32     135   27.91     135
   31.88     135   35.62     135  303.76     135  395.46     135  408.72     135
  421.46     135  482.24  134.76   487.4  129.23   499.5     124     510  119.13
  512.62   118.5  516.35   115.2  522.45  114.24  529.98  113.84   537.3  113.03
  556.51   112.1     558  112.23  568.46  113.38  586.15  119.13   600.1   125.6
  603.41  126.28  613.79  129.87   615.8  134.75     683     135  819.84   135.1
  948.37   135.2  989.43   135.3 1002.06   135.3 1012.82   135.4 1027.75   135.4
BR U #Mann= 3
       0    .092     510     .03   600.1    .092
BR U Banks=510,586.15
BR D #Sta/Elev= 33
       0     135   38.88     135   88.63     135 351.189     135  395.97     135
   406.7   134.9  408.82  129.47     416  128.25  422.03  126.96     437  119.05
  447.08  113.95  452.57   114.5  458.88   112.8  465.84  113.21     485   112.9
   499.2  113.28  499.31  113.28  504.76  117.07  510.46  117.59  513.27  119.26
  520.03  119.26  537.86   129.9  539.47  130.24   541.6   134.9  595.56     135
 612.969     135  616.11     135  802.24     135   805.6     135  824.46     135
 830.849     135  873.74     135 1033.82     135
BR D #Mann= 3
       0    .092     437     .03  520.03    .092
BR D Banks=437,513.27
BC Design=,, 0 ,, 0 ,,,,,,
BC Use User HTab Curves=0
BC User HTab FreeFlow(D)= 0

Type RM Length L Ch R = 1 ,27800.00,235.27,235.5,236.79
XS GIS Cut Line= 2
 1690960.7142413 454379.154133091689957.95692612 454127.64396466
#Sta/Elev= 30
       0  125.22   13.51   125.5   18.25  125.97   28.78  126.47   48.57  126.54
   69.85   125.6  104.23  125.34  118.27  124.67  174.87  124.34  319.53   124.2
  356.53  123.91  422.55  122.65     425     121     430     118     436  117.55
     476  117.55     525     118   535.5  121.39  537.64  123.53  539.44  124.67
  591.38  124.67  595.56  124.85  666.48  124.67  701.64  125.86  729.53  127.95
  779.41  127.95  799.18  129.43  824.46  129.71  873.74  131.23 1033.82  131.23
#Mann= 3 , 0 , 0
       0    .092       0     425     .03       0   535.5    .092       0
#XS Ineff= 2 , 0
       0     407     126     541       0     126
Permanent Ineff=
       F       F
Bank Sta=425,535.5
XS Rating Curve= 0 ,0
Exp/Cntr=0.5,0.3

Type RM Length L Ch R = 1 ,27564.50,180.1,182.94,187.32
XS GIS Cut Line= 2
1691017.88570786 454151.214616091690015.12839268 453899.70444766
#Sta/Elev= 30
       0  126.08   13.18  125.48   21.43  124.97   24.75  124.67   36.84  124.54
  175.29  121.39  189.18  121.39  233.19  123.99  259.45   124.5  264.79  124.67
  271.47  124.67  274.46  124.56  299.02   124.2  319.99  123.96  345.93  123.23
   356.9  123.03   414.2  121.39  437.66  117.05  516.08  117.05  533.12  121.39
  557.57  123.99  562.13  124.67  635.09  124.67  669.74  126.56  699.47  127.95
  712.03  127.95  762.73  131.23  916.13  131.23  979.78  134.51 1033.82  134.51
#Mann= 3 , 0 , 0
       0    .092       0   414.2     .03       0  533.12    .092       0
#XS Ineff= 2 , 0
       0     271     126     746       0     126
Permanent Ineff=
       F       F
Bank Sta=414.2,533.12
XS Rating Curve= 0 ,0
Exp/Cntr=0.3,0.1

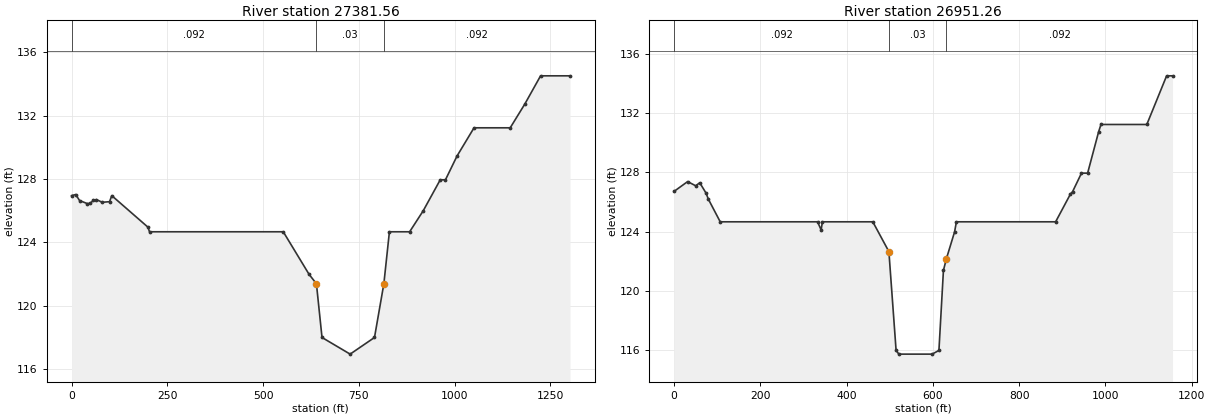
Type RM Length L Ch R = 1 ,27381.56,444.65,430.3,427.31
XS GIS Cut Line= 2
1691319.13933272 453992.616397021690039.74718892 453753.66746361
#Sta/Elev= 30
       0  126.95   10.76  127.02   20.85  126.64   40.87  126.45   48.16  126.46
   56.96  126.65   65.02   126.7   80.04  126.53   99.16  126.57  104.92  126.95
  199.41  124.96  203.44  124.67   552.7  124.67  619.97  121.99   639.3  121.39
  653.88     118  727.34  116.95  790.93     118  815.38  121.39  829.87  124.67
   882.7  124.67  918.27     126  962.61  127.95  976.24  127.95 1006.42  129.45
 1050.81  131.23 1145.31  131.23 1183.45  132.73 1224.61  134.51 1301.51  134.51
#Mann= 3 , 0 , 0
       0    .092       0   639.3     .03       0  815.38    .092       0
Bank Sta=639.3,815.38
XS Rating Curve= 0 ,0
Exp/Cntr=0.3,0.1

Type RM Length L Ch R = 1 ,26951.26,0,0,0
XS GIS Cut Line= 2
1691283.58069168 453591.956572211690162.82403645 453310.84997657
#Sta/Elev= 30
       0  126.72   31.44  127.38      50   127.1   59.59   127.3    74.2   126.6
   79.42   126.2  106.99  124.67  332.66  124.67  340.92  124.12  343.87  124.67
  460.72  124.67  498.01  122.66  514.69     116  521.15  115.75  598.19  115.75
     614     116  624.43  121.39  631.29  122.18  650.27  123.99  654.51  124.67
  884.54  124.67  918.84  126.54  923.79   126.7  944.46  127.95  958.67  127.95
  984.21  130.74  989.62  131.23  1095.9  131.23 1141.81  134.51 1155.47  134.51
#Mann= 3 , 0 , 0
       0    .092       0  498.01     .03       0  631.29    .092       0
Bank Sta=498.01,631.29
XS Rating Curve= 0 ,0
Exp/Cntr=0.3,0.1
LCMann Table=0

Chan Stop Cuts=-1
Use User Specified Reach Order=0
Composite Channel Slope=5

--- HampdenBridges.g02 (geometry) ---

Geom Title=Hampden Bridges 2-Span Proposed
Program Version=5.03

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
River Reach=Souadabscook Str,Reach