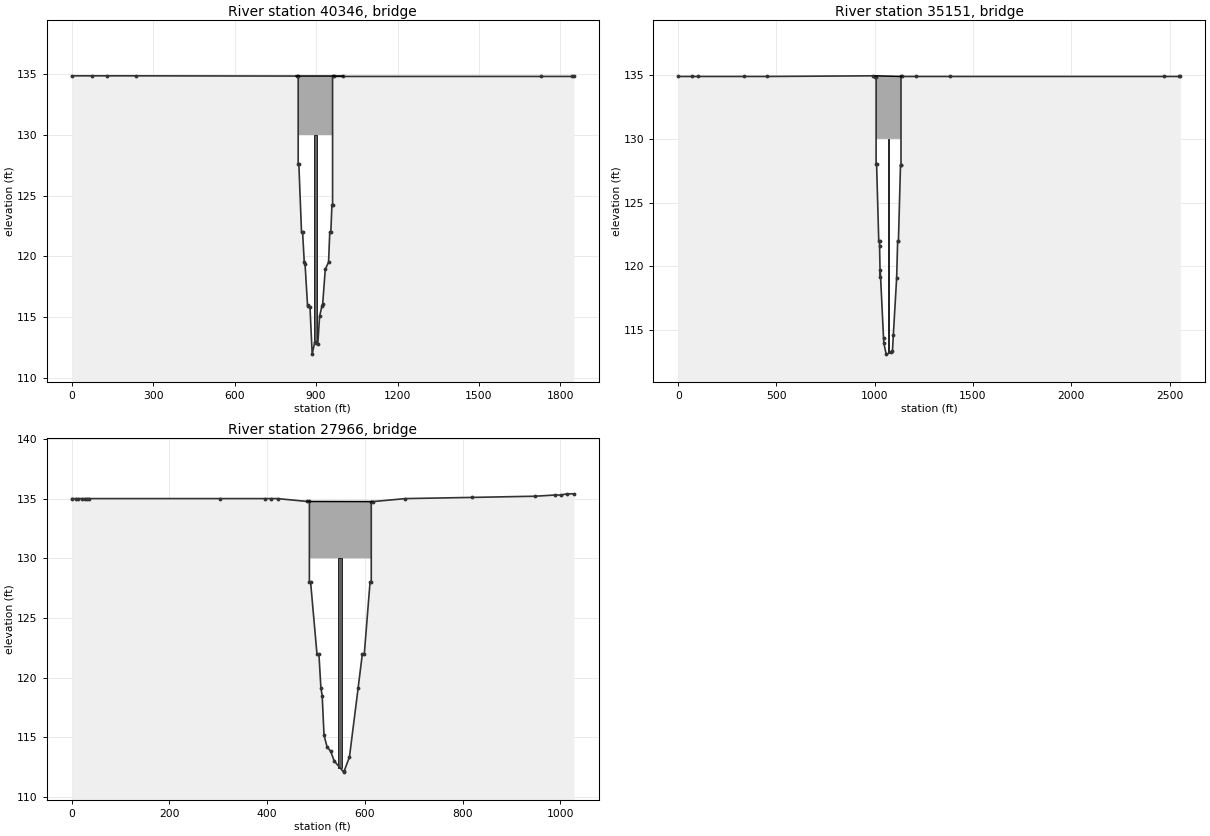
HEC-RAS study HampdenBridges.prj: Hampden Bridges

--- HampdenBridges.g02 (geometry) --- (continued)

Type RM Length L Ch R = 3 ,40346   ,,,
Bridge Culvert--1,0,-1,-1, 0
Deck Dist Width WeirC Skew NumUp NumDn MinLoCord MaxHiCord MaxSubmerge Is_Ogee
62.5,182,2.6,0, 2, 2, , , 0.98, 0, 0,0,,
     825    1000
   134.8   134.8
     130     130
     395     550
   134.8   134.8
     130     130
Pier Skew, UpSta & Num, DnSta & Num=  ,897.305, 4 ,465.605, 4 , 0 , 0 , 0 ,,
     8.5     8.5       5       3
   106.5     113     113   131.1
     8.5     8.5       5       3
   106.5     113     113   131.1
BR Coef=-1 , 1 , 1 ,1.05, 0 ,,,0.8,-1,1.6,0,
WSPro=,,,, 1 ,,,, 0 ,,,, 0 ,,,,-1 ,-1 ,-1 , 0 , 0 , 0 , 0 , 0
BR U #Sta/Elev= 34
       0  134.85   76.18  134.85   128.7  134.85  236.85  134.85  829.23  134.83
833.9717  134.83833.9717  127.57836.4717  127.57846.2217     122850.2217     122
   856.3  119.54   859.3  119.36  868.31  116.01  871.44  115.94  877.35  115.88
  885.52  111.97  894.83  112.95     899   112.9  906.28   112.8  912.81  115.09
  921.39  115.91  924.27  116.11   933.7  118.93  945.87  119.54 950.305     122
 954.305     122958.1383   124.2960.6383   124.2960.6383   134.8  964.22   134.8
 1000.52   134.8  1729.9   134.8 1841.82   134.8 1849.32   134.8
BR U #Mann= 3
       0    .092   856.3     .03 950.305    .092
BR U Banks=856.3,945.87
BR D #Sta/Elev= 37
       0   134.9   49.93   134.9   145.4   134.9  252.88   134.9   330.7   134.9
  397.24   134.9402.2717   134.9402.2717  124.84404.7717  124.84409.7717     122
413.7717     122     424  119.54  424.94  119.27  430.81  116.96  439.61  115.34
  441.33  114.94  447.05   112.9  467.33   112.9  468.88  113.48  476.45  116.27
  485.21  116.47  489.55  116.47  514.88  119.65520.0737     122524.0737     122
526.4383  123.35528.9383  123.35528.9383  134.99   532.1  134.99  585.48  134.99
  642.52  134.99  823.15  134.99  953.98  134.99 1075.68  134.99 1538.67  134.99
 1568.57  134.99 1573.63  134.99
BR D #Mann= 3
       0    .092  424.94     .03520.0737    .092
BR D Banks=424.94,514.88
BC Design=,, 0 ,, 0 ,,,,,,
BC Use User HTab Curves=0
BC User HTab FreeFlow(D)= 0

Type RM Length L Ch R = 3 ,35151   ,,,
Bridge Culvert--1,0,-1,-1, 0
Deck Dist Width WeirC Skew NumUp NumDn MinLoCord MaxHiCord MaxSubmerge Is_Ogee
59,201,2.6,0, 2, 2, , , 0.98, 0, 0,0,,
 1002.19    1137
  134.95   134.9
     130     130
  869.62  1006.6
  134.95   134.9
     130     130
Pier Skew, UpSta & Num, DnSta & Num=  ,1070.235, 4 ,938.985, 4 , 0 , 0 , 0 ,,
     8.5     8.5       5       3
   106.5     113     113  131.25
     8.5     8.5       5       3
   106.5     113     113  131.25
BR Coef=-1 , 1 , 1 ,1.05, 0 ,,,0.8,-1,1.6,0,
WSPro=,,,, 1 ,,,, 0 ,,,, 0 ,,,,-1 ,-1 ,-1 , 0 , 0 , 0 , 0 , 0
BR U #Sta/Elev= 33
       0   134.9   71.06   134.9   102.6   134.9  335.28   134.9  453.98   134.9
  990.31  134.95 1003.64  134.841006.902  134.841006.902     1281009.402     128
1020.402     1221024.402     122 1024.54   121.6  1027.6  119.15 1027.87  119.72
  1044.7  114.38 1046.45  113.96 1058.16  113.11    1085  113.24    1090  113.33
  1094.7  114.65 1111.53  119.111116.568     1221120.568     1221131.068  127.95
1133.568  127.951133.568   134.9    1137   134.9 1211.26   134.9 1381.88   134.9
 2470.65   134.9 2549.63   134.9 2554.96   134.9
BR U #Mann= 3
       0    .092  1027.6  .030921116.568    .092
BR U Banks=1027.6,1111.53
BR D #Sta/Elev= 41
       0  134.95   52.49  134.95   78.43  134.95  256.76  134.95  322.72  134.95
  324.23  134.95  723.42  134.95  819.43  134.95  869.67  134.95  871.63  134.92
875.6517  134.92875.6517  127.69878.1517  127.69888.1517     122892.1517     122
   899.5  121.61  901.86  119.05     912  113.95  914.14  114.12   917.5  114.45
  923.78  112.79  930.74  113.25  942.05  113.18   949.9  112.85  952.62   112.8
  964.09  113.27  964.21  113.28  969.66  117.07  975.36  117.59  978.17  119.26
 985.318     122 989.318     122 999.818  127.981002.318  127.981002.318  134.92
  1006.6  134.92  1009.8  134.95 1233.58     135 1241.08     135  1250.2     135
 1864.66     135
BR D #Mann= 3
       0    .092  901.86     .03 985.318    .092
BR D Banks=901.86,978.17
BC Design=,, 0 ,, 0 ,,,,,,
BC Use User HTab Curves=0
BC User HTab FreeFlow(D)= 0

Type RM Length L Ch R = 3 ,27966   ,,,
Bridge Culvert--1,0,-1,-1, 0
Deck Dist Width WeirC Skew NumUp NumDn MinLoCord MaxHiCord MaxSubmerge Is_Ogee
45,212,2.6,0, 2, 2, , , 0.98, 0, 0,0,,
  482.29   615.8
  134.76  134.75
     130     130
   406.7   541.6
   134.9   134.9
     130     130
Pier Skew, UpSta & Num, DnSta & Num=  ,549.73, 4 ,474.06, 4 , 0 , 0 , 0 ,,
     8.5     8.5       5       3
   106.5     113     113  131.25
     8.5     8.5       5       3
   106.5     113     113  131.25
BR Coef=-1 , 1 , 1 ,1.05, 0 ,,,0.8,-1,1.6,0,
WSPro=,,,, 1 ,,,, 0 ,,,, 0 ,,,,-1 ,-1 ,-1 , 0 , 0 , 0 , 0 , 0
BR U #Sta/Elev= 40
       0     135    8.62     135   11.84     135   21.32     135   27.91     135
   31.88     135   35.62     135  303.76     135  395.46     135  408.72     135
  421.46     135  482.24  134.76486.3967  134.76486.3967     128488.8967     128
501.8967     122505.8967     122     510  119.13  512.62   118.5  516.35   115.2
  522.45  114.24  529.98  113.84   537.3  113.03  556.51   112.1     558  112.23
  568.46  113.38  586.15  119.13594.8133     122598.8133     122610.5633     128
613.0633     128613.0633  134.75   615.8  134.75     683     135  819.84   135.1
  948.37   135.2  989.43   135.3 1002.06   135.3 1012.82   135.4 1027.75   135.4
BR U #Mann= 3
       0    .092     510     .03594.8133    .092
BR U Banks=510,586.15
BR D #Sta/Elev= 38
       0     135   38.88     135   88.63     135 351.189     135  395.97     135
   406.7   134.9410.7267   134.9410.7267     128413.2267     128428.2267     122
432.2267     122     437  119.05  447.08  113.95  452.57   114.5  458.88   112.8
  465.84  113.21     485   112.9   499.2  113.28  499.31  113.28  504.76  117.07
  510.46  117.59  513.27  119.26  520.03  119.26523.8933     122527.8933     122
534.8933  125.93537.3933  125.93537.3933   134.9   541.6   134.9  595.56     135
 612.969     135  616.11     135  802.24     135   805.6     135  824.46     135
 830.849     135  873.74     135 1033.82     135
BR D #Mann= 3
       0    .092     437     .03  520.03    .092
BR D Banks=437,513.27
BC Design=,, 0 ,, 0 ,,,,,,
BC Use User HTab Curves=0
BC User HTab FreeFlow(D)= 0